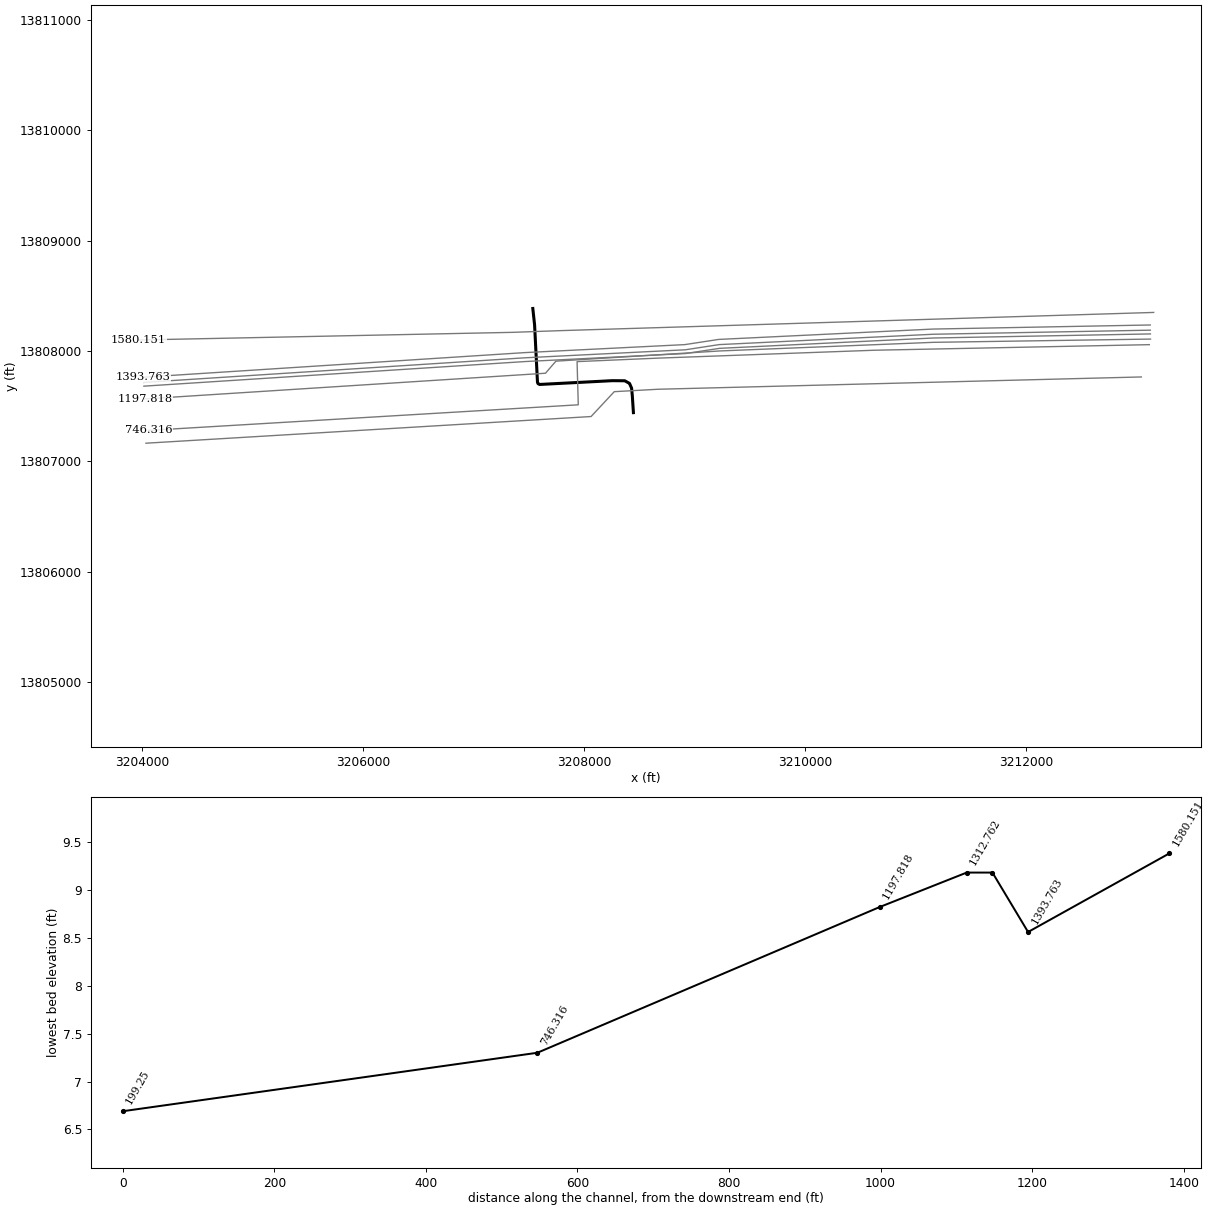
--- B109_03_00.prj (project) ---

Proj Title=B109-03-00
Current Plan=p01
Default Exp/Contr=.3,.1
English Units
Geom File=g01
Geom File=g02
Flow File=f01
Flow File=f02
Plan File=p01
Plan File=p02
Y Axis Title=Elevation
X Axis Title(PF)=Main Channel Distance
X Axis Title(XS)=Station
BEGIN DESCRIPTION:
Armand Bayou
Spring Gully Diversion
HCFCD Unit B109-03-00
Flood Hazard Model
10,2,1,0.2% Event
Filename B109_03_00.prj
Prepared by: Tim Gilboy Date: 5/30/2002
Reviewed by: Christopher Moss Date: 6/15/2004
STATUS FINAL
END DESCRIPTION:
DSS Export Rating Curves= 0
DSS Export Rating Curve Sorted= 0
DSS Export Volume Flow Curves= 0
DXF OffsetX= 0
DXF OffsetY= 0
DXF ScaleX= 1
DXF ScaleY= 10

--- B109_03_00.p01 (plan) ---

Plan Title=FEMA Effective June 2007
Version=Version 3.0.1  Mar 2001
Short Identifier=FEMAeff0607
Geom File=g01
Flow File=f01
Subcritical Flow
K Sum by GR= 0
Std Step Tol= 0.01
Critical Tol= 0.01
Num of Std Step Trials= 20
Max Error Tol= 0.3
Flow Tol Ratio= 0.001
Split Flow NTrial= 30
Split Flow Tol= 0.02
Split Flow Ratio= 0.02
Log Output Level= 0
Friction Slope Method= 0
Unsteady Friction Slope Method= 2
Secant Critical Depth
Global Vel Dist= 0 , 0 , 0
Global Log Level= 0
CheckData=True
Encroach Param=-1 ,0,0, 0
Computation Interval=1HOUR
Output Interval=1HOUR
Run HTab= 0
Run UNet= 0
Run PostProcess= 0
UNET Theta= 1
UNET ZTol= 0.02
UNET ZSATol= 0.1
UNET MxIter= 20
UNET MaxInSteps= 20
UNET DtIC= 0
UNET DtMin= 0
UNET MaxCRTS= 20
UNET WFStab= 2
UNET SFStab= 1
UNET WFX= 1
UNET SFX= 1
UNET Convert EG Bridges=-1
UNET Use Existing IB Tables=-1
Instantaneous Interval=1HOUR
DSS File=dss
Write IC File= 0
Write Velocity= 0
Write Detailed= 0

--- B109_03_00.p02 (plan) ---

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Plan Title=Floodway
Short Identifier=Floodway0607
Geom File=g02
Flow File=f02
Encroach Param=-1 ,0,0, 2
Encroach River=B109-03-00
Encroach Reach=MAIN
Encroach Node=1580.151
       1 4962.61 5037.39
Encroach Node=1393.763
       1 4959.43 5040.57
Encroach Node=1346.762
       1 4939.72  5094.1
Encroach Node=1329.763
       1 4939.72  5094.1
Encroach Node=1312.762
       1 4940.06 5089.46
Encroach Node=1197.818
       1 4951.72 5049.46
Encroach Node=746.316
       1 4953.21 5046.79
Encroach Node=199.25
       1 4939.66 5060.34
Encroach Reach=B109-03-00_0002
Encroach Node=1580.151
       1 4962.61 5037.39
Encroach Node=1393.763
       1 4959.43 5040.57
Encroach Node=1346.762
       1 4939.72  5094.1
Encroach Node=1329.763
       1 4939.72  5094.1
Encroach Node=1312.762
       1 4940.06 5089.46
Encroach Node=1197.818
       1 4951.72 5049.46
Encroach Node=746.316
       1 4953.21 5046.79
Encroach Node=199.25
       1 4939.66 5060.34

--- B109_03_00.f01 (steady flow) ---

Flow Title=FEMA Effective June 2007
Version=Version 3.0.1  Mar 2001
Number of Profiles= 4
Profile Names=10PCT_10yr, 2PCT_50yr, 1PCT_100yr, 0.2PCT_500yr
River Rch & RM=Spring Div,Main            ,1580.151
     576     815     935    1289
River Rch & RM=B109-03-00,B109-03-00_0002            ,1580.151
     576     815     935    1289
Boundary for River Rch & Prof#=B109-03-00,B109-03-00_0002            , 1
Up Type= 0
Dn Type= 3
Dn Slope=.002
Boundary for River Rch & Prof#=B109-03-00,B109-03-00_0002            , 2
Up Type= 0
Dn Type= 3
Dn Slope=.002
Boundary for River Rch & Prof#=B109-03-00,B109-03-00_0002            , 3
Up Type= 0
Dn Type= 3
Dn Slope=.002
Boundary for River Rch & Prof#=B109-03-00,B109-03-00_0002            , 4
Up Type= 0
Dn Type= 3
Dn Slope=.002
DSS Import GetInterval= 0
DSS Import GetPeak= 0
DSS Import FillOption= 0

--- B109_03_00.f02 (steady flow) ---

Flow Title=Floodway
Version=Version 3.0.1  Mar 2001
Number of Profiles= 2
Profile Names=1PCT_100yr, 1PCTFloodway_100yrFW
River Rch & RM=B109-03-00,B109-03-00_0002            ,1580.151
     935     935
Boundary for River Rch & Prof#=B109-03-00,B109-03-00_0002            , 1
Up Type= 0
Dn Type= 3
Dn Slope=.002
Boundary for River Rch & Prof#=B109-03-00,B109-03-00_0002            , 2
Up Type= 0
Dn Type= 3
Dn Slope=.002
DSS Import GetInterval= 0
DSS Import GetPeak= 0
DSS Import FillOption= 0

--- B109_03_00.g01 (geometry) ---

Geom Title=B109-03-00 June 2007
Version=Version 3.0.1  Mar 2001

River Reach=B109-03-00      ,B109-03-00_0002
Reach XY= 30
      3207535.32    13808384.155     3207551.393    13808235.923
      3207563.76    13807990.152     3207565.792    13807949.786
     3207566.569    13807934.328     3207569.927    13807867.614
     3207571.308    13807840.152     3207574.328    13807780.152
     3207575.025    13807766.284     3207577.528     13807716.56
     3207582.393    13807703.586     3207596.989    13807696.288
     3207713.939     13807702.37     3207816.157    13807707.687
     3207844.685     13807709.17     3207870.782    13807710.528
     3207979.164    13807716.164     3208041.408    13807719.402
     3208103.644    13807722.638     3208161.157     13807725.63
      3208240.35    13807729.748     3208254.948    13807730.508
     3208368.263    13807729.592     3208411.079    13807705.666
     3208411.305    13807705.152     3208417.382    13807691.377
     3208419.317    13807686.993     3208429.968     13807662.85
     3208436.264    13807597.368       3208446.5       13807441.

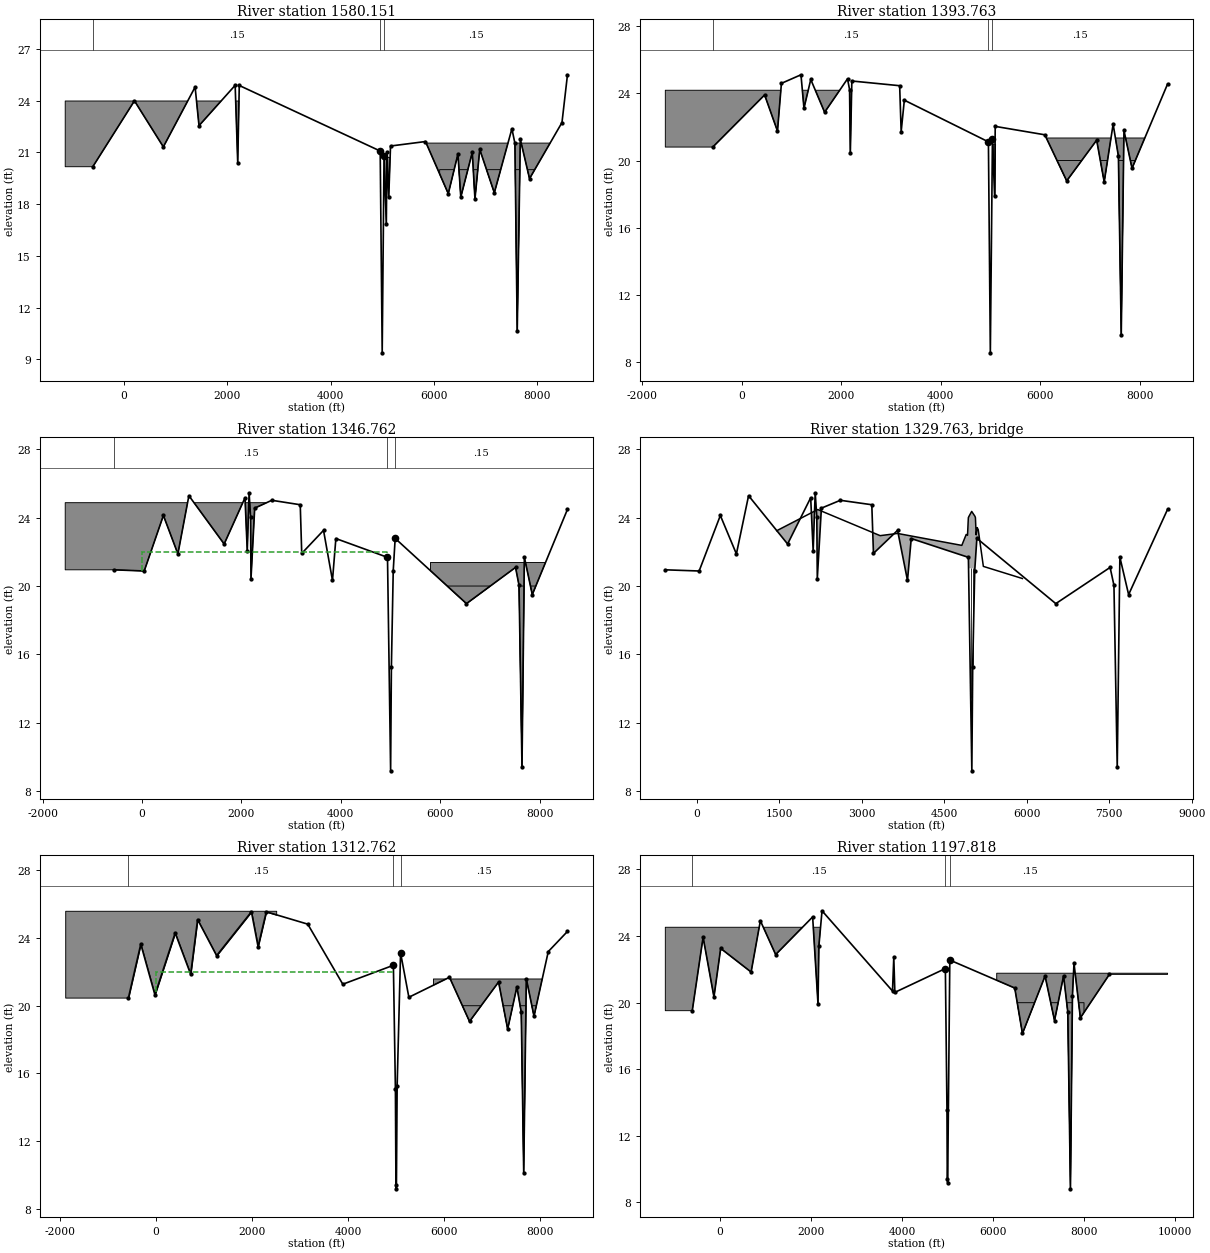
Type RM Length L Ch R = 1 ,1580.151,184.6,186.39,188.78
XS GIS Cut Line= 4
     3213158.618    13808348.532     3207787.764     13808183.79
     3207351.911    13808168.224     3203962.633    13808098.954
#Sta/Elev= 30
 -607.09   20.17  200.22   23.99  760.04   21.32 1375.82   24.79 1451.34   22.55
 2151.96   24.89 2201.68    20.4  2231.7   24.88 4962.61   21.08 5001.65    9.38
 5037.39   20.81 5081.64   16.87 5093.44   21.01 5128.12    18.4 5162.98   21.37
  5840.8   21.63  6282.3   18.61  6469.5    20.9 6524.88   18.41 6747.62      21
 6799.26    18.3 6892.44   21.17  7174.7   18.66 7515.44   22.37 7573.66   21.53
 7618.68   10.64 7678.68   21.76 7856.96   19.48 8485.86   22.73  8592.4    25.5
#Mann= 3 ,-1 , 0
 -607.09     .15       0 4962.61    .035       0 5037.39     .15       0
#Block Obstruct= 5 ,-1
 -1141.7 2615.38   23.98    4895    4957    20.9 5789.47 8655.87   21.54
    6115    8000      20    5038    5155    20.7
Bank Sta=4962.61,5037.39
XS Rating Curve= 0
Exp/Cntr=.3,.1

Type RM Length L Ch R = 1 ,1393.763,47,47,47.01
XS GIS Cut Line= 6
     3213127.516    13808234.947     3211159.645    13808197.979
     3209218.017    13808104.058     3208912.307    13808057.135
      3207463.06    13807984.725     3204007.502    13807761.708
#Sta/Elev= 30
 -577.07    20.8  464.19    23.9  722.59   21.75  801.57   24.59 1194.35    25.1
 1254.61   23.11 1391.23   24.82 1669.65   22.87 2129.31   24.86 2170.54   24.22
 2185.55   20.42 2216.23   24.73 3176.82   24.45 3206.84   21.72 3270.61   23.59
 4959.43   21.11 4998.07    8.56 5040.57   21.29 5083.91   17.87 5096.25   22.03
 6092.21   21.53 6532.09   18.79 7133.89   21.21 7285.16   18.73 7464.64   22.16
 7570.45   20.26  7627.6    9.62 7681.96   21.79 7844.31   19.54 8558.18   24.55
#Mann= 3 ,-1 , 0
 -577.07     .15       0 4959.43    .035       0 5040.57     .15       0
#Block Obstruct= 4 ,-1
-1530.36 2631.58   24.18 5821.86 9012.15   21.34    6195    8000      20
    5043    5142      21
Bank Sta=4959.43,5040.57
XS Rating Curve= 0
Exp/Cntr=.5,.3

Type RM Length L Ch R = 1 ,1346.762,34,34,34
XS GIS Cut Line= 6
     3213128.399    13808187.956     3211161.216       13808151.
      3209222.46    13808057.189     3208916.865    13808010.284
     3207465.641    13807937.794     3204010.529    13807714.806
#Sta/Elev= 30
  -571.2   20.95   43.67   20.88  429.34   24.13  721.28   21.88  942.66   25.29
 1652.42   22.46 2072.18   25.17 2117.22   22.06 2154.32   25.46 2183.28   24.05
 2192.32   20.43  2266.9   24.56 2611.16   25.02 3183.58   24.76  3213.6   21.91
 3652.26   23.26 3832.42   20.33 3900.68   22.78 4939.72   21.68 5002.59    9.18
 5018.15   15.27 5055.05    20.9  5094.1   22.79 6529.18   18.97 7516.82   21.09
 7586.78   20.04 7646.52    9.38 7694.48   21.69  7853.5    19.5 8561.92   24.49
#Mann= 3 ,-1 , 0
  -571.2     .15       0 4939.72    .035       0  5094.1     .15       0
#XS Ineff= 2 , 0
       0    4939      22    5070       0      20
Permanent Ineff=
       F       F
#Block Obstruct= 3 ,-1
-1546.56 2647.77   24.88 5805.67  8866.4   21.38    6150    8000      20
Bank Sta=4939.72,5094.1
XS Rating Curve= 0
Exp/Cntr=.5,.3

Type RM Length L Ch R = 3 ,1329.763,,,
BEGIN DESCRIPTION:
B109S1
END DESCRIPTION:
Bridge Culvert--1,0,-1,-1, 0
Deck Dist Width WeirC Skew NumUp NumDn MinLoCord MaxHiCord MaxSubmerge Is_Ogee
1,32,2.6,0, 17, 17, , , .95, 0, 0,0,,
    1455    2200    3335    3650    4820    4900    4924    4939    4947    5000
    5060    5068    5081    5100    5119    5212    5922
   23.24   24.48   22.95   23.08   22.38   23.02   22.97      24   24.06   24.37
   24.08      24      23   23.42    23.3   21.15   20.44
                                                           21.04   21.04   21.04
   21.04   21.04   21.04
    1455    2200    3335    3650    4820    4900    4924    4939    4947    5000
    5060    5068    5081    5100    5119    5212    5922
   23.24   24.48   22.95   23.08   22.38   23.02   22.97      24   24.06   24.37
   24.08      24      23   23.42    23.3   21.15   20.44
                                                           21.04   21.04   21.04
   21.04   21.04   21.04
Pier Skew, UpSta & Num, DnSta & Num=  ,4981, 4 ,4981, 4 , 3 , 3 , 0 ,,
    1.35    1.35       2       2
       8   19.04   19.04   21.04
    1.35    1.35       2       2
       8   19.04   19.04   21.04
Pier Skew, UpSta & Num, DnSta & Num=  ,5019, 4 ,5019, 4 , 3 , 3 , 0 ,,
    1.35    1.35       2       2
       8   19.04   19.04   21.04
    1.35    1.35       2       2
       8   19.04   19.04   21.04
BR Coef=-1 , 1 , 0 ,, 0 ,,,.8,-1,2,0,
WSPro=,,,, 1 ,,,, 0 ,,,, 0 ,,,,-1 ,-1 ,-1 , 0 , 0 , 0 , 0 , 0
BC Design=,, 0 ,, 0 ,,,,,,

Type RM Length L Ch R = 1 ,1312.762,37.23,114.94,116.01
XS GIS Cut Line= 6
     3213129.038    13808153.962     3211162.353    13808117.015
     3209225.675    13808023.284     3208920.162    13807976.392
     3207467.508    13807903.843     3204012.719    13807680.876
#Sta/Elev= 30
 -570.25   20.48 -314.72   23.64  -20.31   20.64  400.82    24.3  722.86   21.86
  867.35   25.09 1262.95   22.96 1986.91   25.55 2125.39   23.49 2296.29   25.55
 3158.72   24.82 3887.93   21.27 4940.06   22.39 4981.98   15.08 4993.37     9.4
 5002.59    9.18 5018.15   15.27 5089.46   23.12 5262.05    20.5 6106.97   21.68
 6524.03   19.07 7128.26    21.4 7317.19   18.62 7508.83   21.11 7599.81   19.62
 7650.98   10.14 7705.53   21.59  7865.2   19.38 8162.04    23.2 8561.31   24.39
#Mann= 3 ,-1 , 0
 -570.25     .15       0 4940.06    .035       0 5089.46     .15       0
#XS Ineff= 2 , 0
       0    4939      22    5070       0      20
Permanent Ineff=
       F       F
#Block Obstruct= 3 ,-1
-1886.64 2502.02   25.61 5773.28  8866.4   21.58    6135    8000      20
Bank Sta=4940.06,5089.46
XS Rating Curve= 0
Exp/Cntr=.5,.3

Type RM Length L Ch R = 1 ,1197.818,216.09,451.5,707.07
XS GIS Cut Line= 6
     3213129.864    13808107.235     3211162.246    13808077.773
     3209232.508     13807999.91     3207744.695    13807907.317
     3207649.997    13807797.888      3204020.19    13807565.117
#Sta/Elev= 30
 -613.74   19.52  -375.6   23.93 -136.74   20.34   10.95   23.26  680.11   21.84
   883.6   24.92    1220   22.89 2033.28   25.15 2150.86   19.93 2170.48   23.41
  2239.4   25.52 3789.42    20.7 3817.56   22.72  3841.2   20.62 4951.72   22.05
 4986.99   13.57 4993.37     9.4 5002.59    9.18 5049.46   22.56  6477.4   20.88
 6646.76   18.15 7144.12    21.6  7352.4   18.93  7550.9   21.61 7643.78   19.44
 7702.22    8.82 7746.38   20.42 7780.16   22.37 7920.66   19.09 8559.04    21.7
#Mann= 3 ,-1 , 0
 -613.74     .15       0 4951.72    .035       0 5049.46     .15       0
#Block Obstruct= 3 ,-1
-1206.48 2453.44   24.53 6080.97 9838.06   21.77    6130    8000      20
Bank Sta=4951.72,5049.46
XS Rating Curve= 0
Exp/Cntr=.3,.1

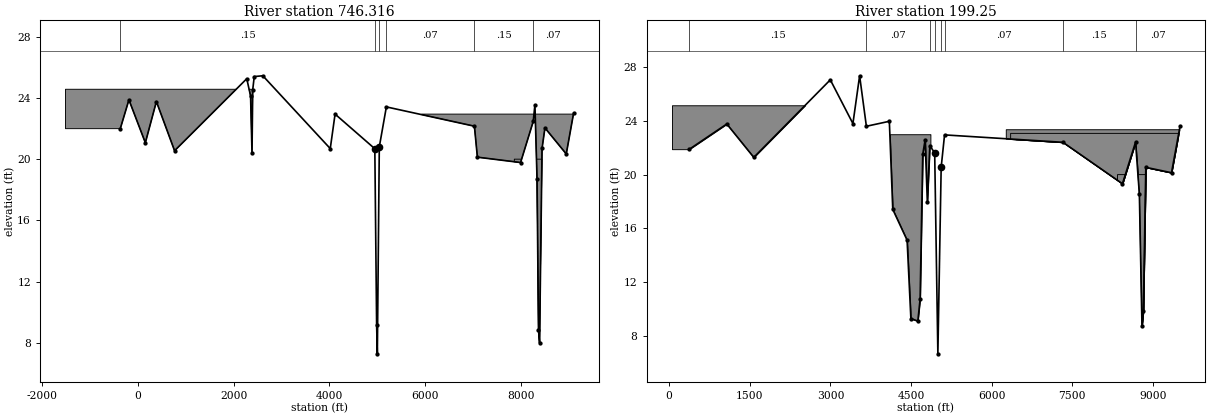
Type RM Length L Ch R = 1 ,746.316 ,799.64,547.07,252.64
XS GIS Cut Line= 6
     3213119.342    13808056.729     3210629.832    13808006.224
     3208668.528    13807934.674     3207936.196    13807903.108
     3207947.101    13807511.976     3204054.165    13807280.014
#Sta/Elev= 30
  -368.6   21.99 -188.22   23.87  155.42   21.07  386.16   23.76  766.32   20.55
 2275.96   25.25 2355.26   24.12 2385.28    20.4 2400.28   24.53 2432.14   25.39
 2611.62   25.44 4021.36   20.69 4122.12   22.94 4953.21   20.68 4990.91    9.16
 5005.93     7.3 5046.79    20.8 5194.48   23.41 7035.42   22.15 7097.64   20.13
 8000.74   19.78 8265.24   22.46 8300.82   23.55 8344.84    18.7  8374.9    8.88
 8397.82    8.02 8450.04    20.7 8509.92   22.04 8956.08   20.34  9108.2   22.98
#Mann= 6 ,-1 , 0
  -368.6     .15       0 4953.21    .035       0 5046.79     .15       0
 5194.48     .07       0 7035.42     .15       0 8265.24     .07       0
#Block Obstruct= 3 ,-1
-1514.17 2534.41   24.56 5935.22 9368.42   22.94    7870    8525      20
Bank Sta=4953.21,5046.79
XS Rating Curve= 0
Exp/Cntr=.3,.1

Type RM Length L Ch R = 1 ,199.25  ,196.07,199.25,216.31
XS GIS Cut Line= 5
     3213046.915    13807764.267     3208670.666    13807652.864
     3208273.165    13807630.955     3208062.967    13807405.745
     3204031.473     13807164.19
#Sta/Elev= 30
  379.42   21.89 1073.58   23.76 1575.36   21.28 2998.54   27.04    3419   23.79
 3543.54   27.34 3669.34   23.59 4096.38   23.96 4159.96   17.42  4426.5   15.13
 4496.96    9.31  4626.3    9.12  4669.1   10.77 4717.88   21.51 4761.64   22.57
 4803.22   17.95 4849.48   22.15 4939.66   21.61  4998.8    6.69 5060.34   20.55
 5123.16   22.95 7325.32    22.4  8431.7   19.32 8674.94   22.41 8745.94   18.57
 8794.68    8.79 8821.08     9.9 8866.16   20.54 9343.66   20.14 9501.98   23.58
#Mann= 8 ,-1 , 0
  379.42     .15       0 3669.34     .07       0 4849.48     .15       0
 4939.66    .035       0 5060.34     .15       0 5123.16     .07       0
 7325.32     .15       0 8674.94     .07       0
#Block Obstruct= 6 ,-1
   53.98 2941.97   25.15    4080    4860      23 6261.81 9649.12   23.37
  6288.8  9716.6   22.62 6342.78 9581.65    23.1    8340    9410      20
Bank Sta=4939.66,5060.34
XS Rating Curve= 0
Exp/Cntr=.3,.1

Chan Stop Cuts=-1

--- B109_03_00.g02 (geometry) ---

Geom Title=B109-03-00 June 2007 (Floodway)
Version=Version 3.0.1  Mar 2001

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
River Reach=B109-03-00      ,B109-03-00_0002